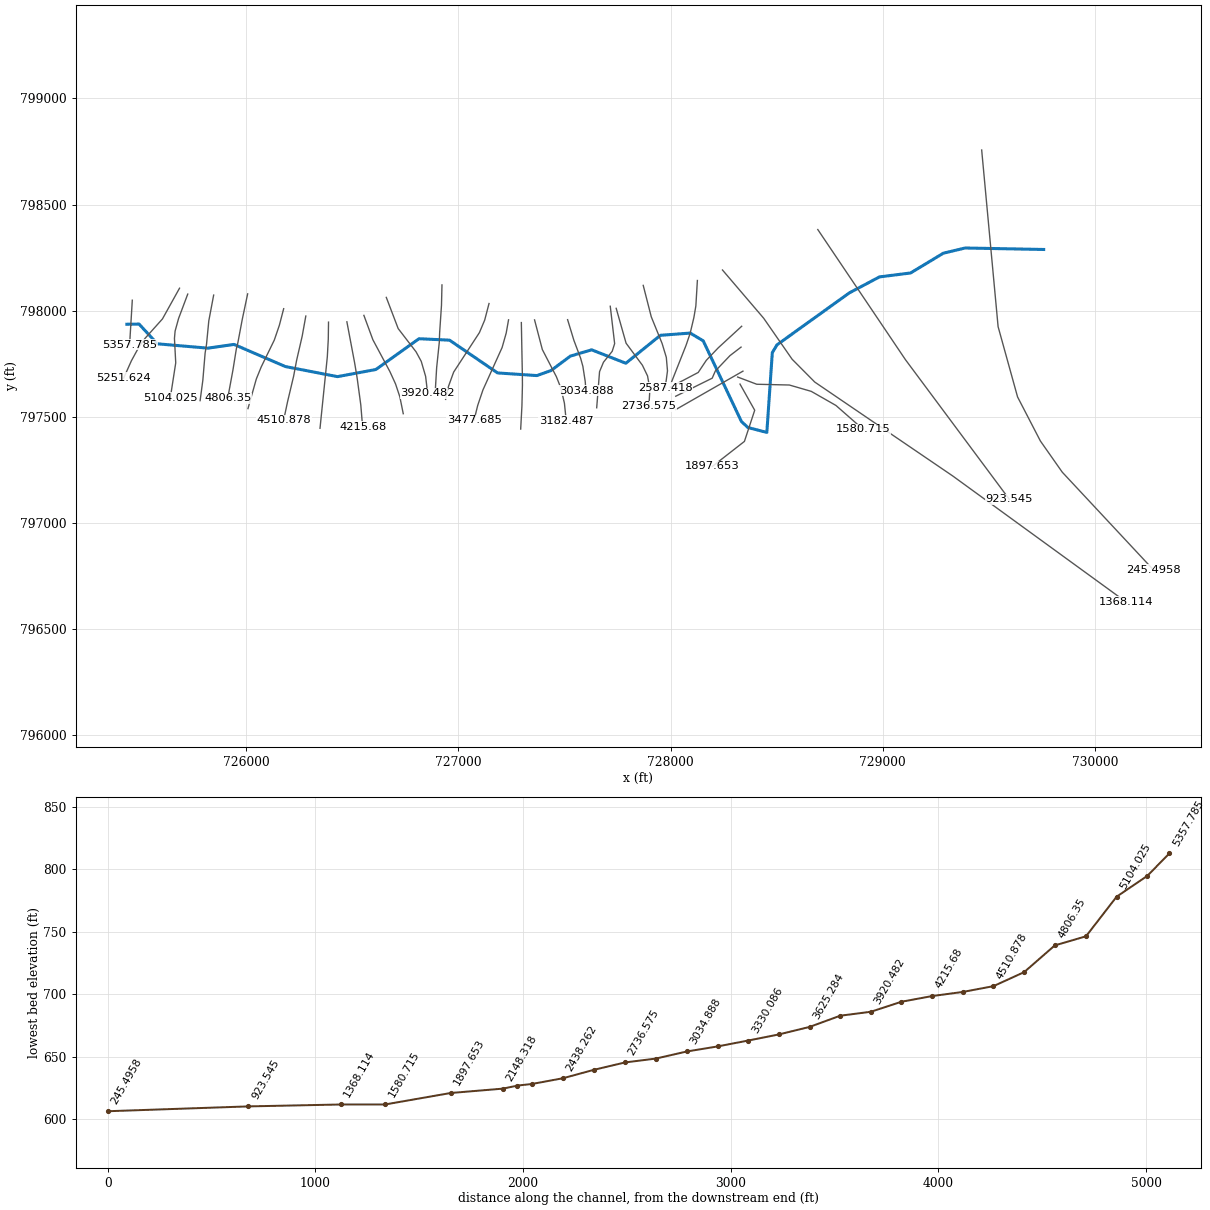
--- 14650_ras.prj (project) ---

Proj Title=14650
Current Plan=p01
Default Exp/Contr=0.3,0.1
English Units
Geom File=g01
Flow File=f01
Plan File=p01
Y Axis Title=Elevation
X Axis Title(PF)=Main Channel Distance
X Axis Title(XS)=Station
BEGIN DESCRIPTION:
RFD model 14650 exported to HEC-RAS
END DESCRIPTION:

--- 14650_ras.p01 (plan) ---

Plan Title=Plan 01
Program Version=4.10
Short Identifier=Plan 01
Geom File=g01
Flow File=f01
Subcritical Flow
Calc Critical at every XS
Secant Critical Depth

--- 14650_ras.f01 (steady flow) ---

Flow Title=Flow 01
Program Version=5.01
Number of Profiles= 6
Profile Names=10yr,25yr,50yr,100yr,100plus,500yr
River Rch & RM=14650,29,5357.785
  446.68  780.76  1117.6  1456.4 2126.35 3517.63
River Rch & RM=14650,29,5251.624
  448.13  783.36 1121.38 1461.41 2133.66 3528.41
River Rch & RM=14650,29,5104.025
  449.14  785.19 1124.06 1464.97 2138.85 3536.11
River Rch & RM=14650,29,4956.426
   453.6  793.24 1135.84 1480.58 2161.65  3569.9
River Rch & RM=14650,29, 4806.35
  583.25  1022.1 1465.88 1912.84 2792.75 4457.55
River Rch & RM=14650,29,4658.477
  583.82 1023.15 1467.41 1914.86  2795.7 4461.76
River Rch & RM=14650,29,4510.878
  593.57 1040.77 1493.21 1949.12 2845.71 4533.17
River Rch & RM=14650,29,4363.279
  594.91 1043.18 1496.75 1953.81 2852.57 4542.93
River Rch & RM=14650,29, 4215.68
  599.67  1051.8 1509.36 1970.55 2877.01 4577.74
River Rch & RM=14650,29,4068.081
  603.28 1058.32 1518.92 1983.24 2895.54 4604.13
River Rch & RM=14650,29,3920.482
  606.53 1064.19  1527.5 1994.62 2912.15 4627.69
River Rch & RM=14650,29,3772.883
  624.81 1096.99  1575.3 2057.81 3004.41 4757.12
River Rch & RM=14650,29,3625.284
  628.02 1102.79  1583.8 2069.09 3020.87 4780.38
River Rch & RM=14650,29,3477.685
   629.9  1106.2 1588.78 2075.71 3030.53 4794.04
River Rch & RM=14650,29,3330.086
  632.71 1111.28 1596.23 2085.61 3044.99  4814.5
River Rch & RM=14650,29,3182.487
  637.79 1120.46 1609.68 2103.45 3071.04 4851.25
River Rch & RM=14650,29,3034.888
  647.89 1138.64 1636.23  2138.6 3122.36 4923.07
River Rch & RM=14650,29,2885.732
  650.69  1143.7 1643.64 2148.45 3136.74 4943.33
River Rch & RM=14650,29,2736.575
  652.18  1146.4 1647.59  2153.7 3144.41 4954.11
River Rch & RM=14650,29,2587.418
   702.6 1236.62 1778.87 2326.97 3397.37 5302.51
River Rch & RM=14650,29,2438.262
  703.89 1238.95 1782.28  2331.5 3403.99  5311.7
River Rch & RM=14650,29,2289.105
  704.44 1239.95 1783.75 2333.44 3406.82 5315.63
River Rch & RM=14650,29,2218.517
  705.54 1241.94 1786.66 2337.31 3412.48 5323.49
River Rch & RM=14650,29,1897.653
   710.1  1250.2 1798.77 2353.41 3435.98 5356.21
River Rch & RM=14650,29,1580.715
  706.64 1243.92 1789.57 2341.18 3418.12 5331.35
River Rch & RM=14650,29,1368.114
  705.54 1241.94 1786.66 2337.31 3412.48 5323.49
River Rch & RM=14650,29, 923.545
  704.44 1239.95 1783.75 2333.44 3406.82 5315.63
River Rch & RM=14650,29,245.4958
  705.54 1241.94 1786.66 2337.31 3412.48 5323.49
Boundary for River Rch & Prof#=14650,29,1
Up Type= 0
Dn Type= 2
Boundary for River Rch & Prof#=14650,29,2
Up Type= 0
Dn Type= 2
Boundary for River Rch & Prof#=14650,29,2
Up Type= 0
Dn Type= 2
Boundary for River Rch & Prof#=14650,29,2
Up Type= 0
Dn Type= 2
Boundary for River Rch & Prof#=14650,29,2
Up Type= 0
Dn Type= 2
Boundary for River Rch & Prof#=14650,29,2
Up Type= 0
Dn Type= 2

--- 14650_ras.g01 (geometry) ---

Geom Title=14650
Program Version=4.10

River Reach=14650,29
Reach XY= 30
725438.321916779797936.127838062725495.455091268797937.025217757
725581.427313507797843.900217742 725819.76064682797823.483551055
 725942.97593388797841.030955374726184.816202402797736.733551085
726430.649535745 797689.23355107726611.205091298 797722.84466216
726814.538424641797867.844662175726958.427313507797861.177995533
727184.816202343797706.733551085727369.816202343 797694.23355107
727436.205091298797717.566884398727528.149535716797786.177995518
727628.149535686797815.622439951 727789.26064685797752.289106637
727952.038424611797883.955773279728092.593980134797894.511328846
728153.982869089797857.844662175728333.982869089797477.844662189
728364.538424641797449.511328861728453.750242829797426.332893014
 728479.52614215797802.308405742728501.528880537797838.977083072
728842.355115205798083.834816992 728984.36900416798159.182039201
729130.757892996 798177.65426141729285.757893026798270.987594739
729388.535670757798295.432039157729758.227466226798288.437435821

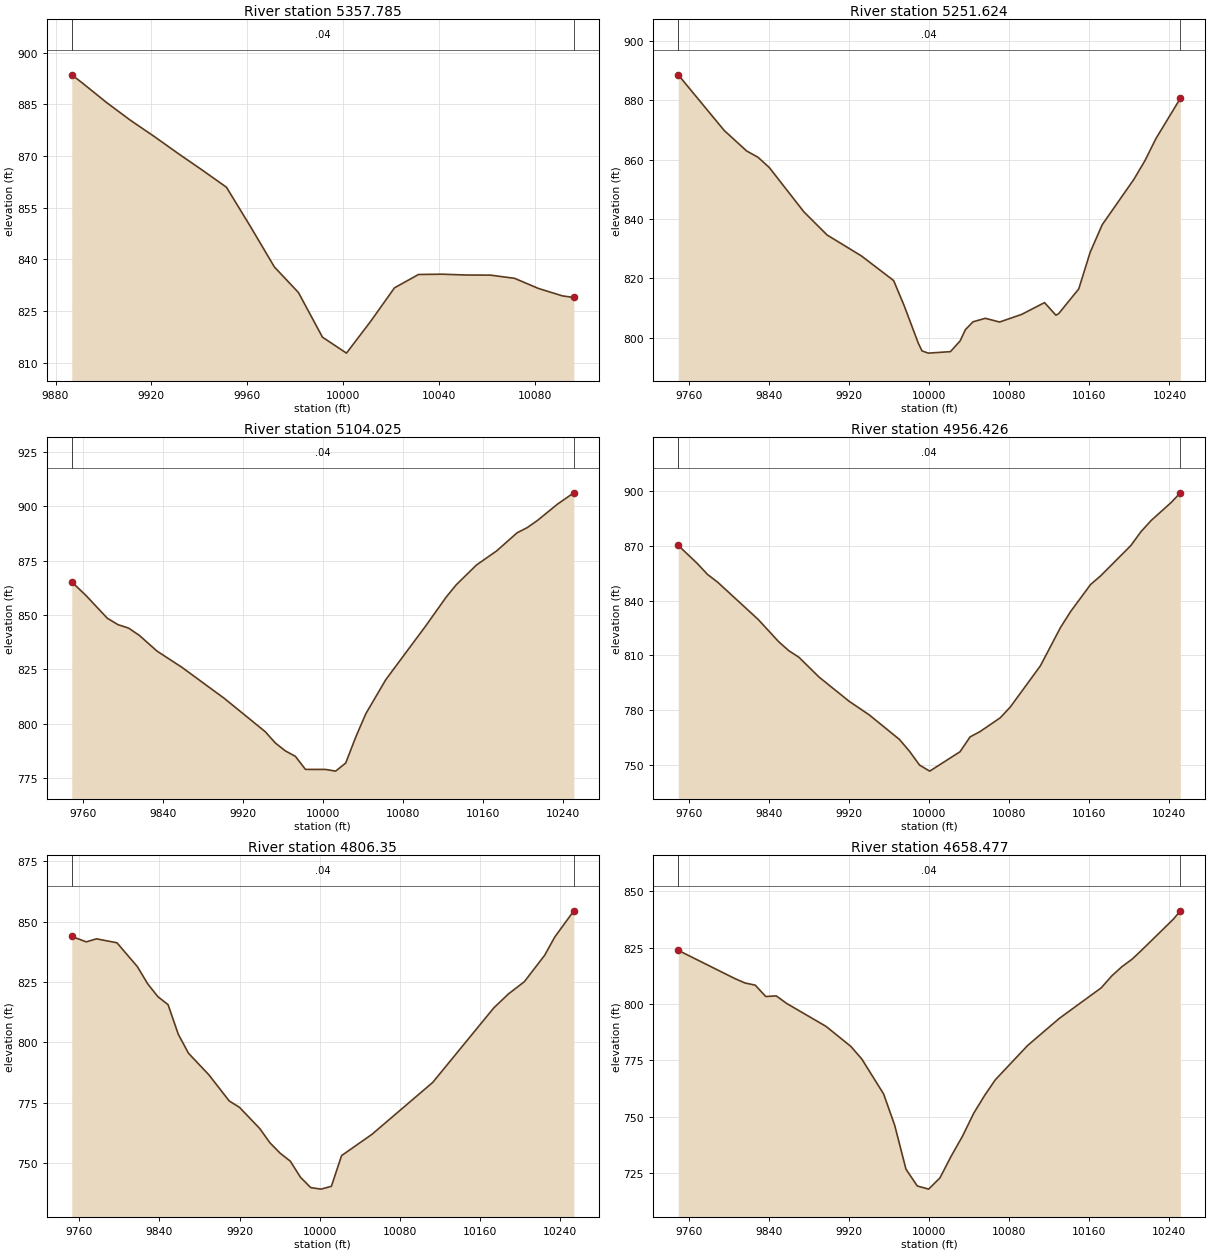
Type RM Length L Ch R = 1 ,5357.785,106.160900,106.160900,106.160900
XS GIS Cut Line= 2
725463.637514174798049.435017362725450.984211892797840.283373684
#Sta/Elev= 24
9886.776893.5471 9891.22891.16799901.238885.54129911.256880.36089921.274875.6181
9931.293870.65989941.311865.86269951.329860.93079961.348849.52089971.366837.7624
9981.384830.36059991.402817.413210001.42812.782410011.44821.937410021.46831.7345
10029.81834.949510031.48 835.60810041.49835.686510051.51835.450110061.53835.4176
10071.55834.495310081.57831.543910091.59829.388810096.31828.9304
#Mann= 3 , 0 , 0
9886.776    0.04       09886.776    0.04       010096.31    0.04       0
#XS Ineff= 2 , 0
       0                               0
Bank Sta=9886.776,10096.31
Exp/Cntr=0.3,0.1

Type RM Length L Ch R = 1 ,5251.624,147.598900,147.598900,147.598900
XS GIS Cut Line= 6
725686.217203347798106.015052245725605.708586328797961.128269351
725524.117240645797870.137771505725495.690808605797830.368591497
725459.432966604797764.034808681725423.117343518797682.770170641
#Sta/Elev= 30
9749.079888.59929795.069869.82539817.495862.91879828.708860.83479840.058857.3616
9874.687842.39569897.877834.59989932.249827.52539964.355819.24569974.902810.7783
9989.002798.15559992.723795.5329    9999794.773510021.16795.275310030.86798.9127
10036.09 802.68710043.73805.335610056.02806.515510070.29805.259110092.41807.8461
10115.21811.8023 10126.6 807.54310129.43808.131110149.39 816.41810160.79828.7666
10172.76838.015810204.65853.4415 10215.6859.694610226.55867.1147 10250.9880.6471
#Mann= 3 , 0 , 0
9749.079    0.04       09749.079    0.04       0 10250.9    0.04       0
#XS Ineff= 2 , 0
       0                               0
Bank Sta=9749.079,10250.9
Exp/Cntr=0.3,0.1

Type RM Length L Ch R = 1 ,5104.025,147.598900,147.598900,147.598900
XS GIS Cut Line= 6
 725724.92048741798078.262323112725681.759289264  797963.2941523
725665.294956085797903.659713966725662.251620464 797869.02632377
725668.330178697797754.188296221 725642.73594638797589.106725192
#Sta/Elev= 30
9749.103865.22499763.269859.01439784.632848.52549795.313845.56819805.995843.9657
9816.676840.61859834.233833.42999859.402825.86639901.569811.63439942.505796.2908
9952.544791.10379962.582787.45729972.624 784.9439982.671778.940710002.78778.9289
10012.84778.144810022.91781.884810032.97793.864610042.98804.543110062.98820.2599
10103.12845.133210123.26858.215310133.34863.899810153.48872.979410173.79879.5326
10194.12887.819410204.28890.225410214.44893.490410234.77901.115810250.92906.2508
#Mann= 3 , 0 , 0
9749.103    0.04       09749.103    0.04       010250.92    0.04       0
#XS Ineff= 2 , 0
       0                               0
Bank Sta=9749.103,10250.92
Exp/Cntr=0.3,0.1

Type RM Length L Ch R = 1 ,4956.426,150.076200,150.076200,150.076200
XS GIS Cut Line= 6
725847.040831077798073.479399903725824.147315635797952.090921809
 725813.40721238797841.830643636725806.713861128797799.594767359
725796.002892539797671.696240208725783.215876202797576.074356254
#Sta/Elev= 30
9749.032870.27879767.927860.45479778.151854.42819788.376850.1278 9829.14829.5638
9849.397 817.4659859.525812.53359869.654808.92739889.772798.05969919.914784.7385
9940.009777.27589970.151763.82849980.198757.36399990.305749.743110000.45746.4297
10030.76757.0721 10040.8 765.21410050.83768.1516 10070.9775.668510080.94781.5652
10111.04804.164610131.11825.152910141.15833.875810161.25848.823510171.34853.5815
10201.61870.2724 10211.7877.855910221.79883.939410241.96893.887510250.97899.1321
#Mann= 3 , 0 , 0
9749.032    0.04       09749.032    0.04       010250.97    0.04       0
#XS Ineff= 2 , 0
       0                               0
Bank Sta=9749.032,10250.97
Exp/Cntr=0.3,0.1

Type RM Length L Ch R = 1 , 4806.35,147.873200,147.873200,147.873200
XS GIS Cut Line= 6
726007.201904702798079.214553907725981.704003185797958.409654067
725961.165939652 797849.34050702725954.060558815797820.950645051
 725937.81332514797719.808200157725913.074623429797586.263638026
#Sta/Elev= 30
9752.294843.89659766.822841.65029777.042842.90719797.483841.27019817.923831.3669
9828.144824.29069838.364  818.939848.584815.61449858.805803.32769869.025795.4566
9889.406786.52129909.757775.66899919.933773.06539940.285764.2288 9950.46758.3229
9960.636 754.0289970.812750.72199980.988744.03179991.218739.762810001.52 739.132
10011.85740.292710022.04753.023510052.43761.8518 10113.2783.3859 10174.2814.2604
 10188.8820.035710204.71825.098110225.05836.064710235.22843.677910254.27854.5181
#Mann= 3 , 0 , 0
9752.294    0.04       09752.294    0.04       010254.27    0.04       0
#XS Ineff= 2 , 0
       0                               0
Bank Sta=9752.294,10254.27
Exp/Cntr=0.3,0.1

Type RM Length L Ch R = 1 ,4658.477,147.598900,147.598900,147.598900
XS GIS Cut Line= 6
726176.989048662798009.501282027726156.661536445797931.407886677
726132.836613104797861.654338887726070.673869374797733.966943392
726047.957220267797677.878252921726008.701857308797538.488145621
#Sta/Elev= 30
9749.058823.83559805.375811.35899815.708809.34269826.042808.36619836.525803.3243
9847.092803.58669857.659800.1843 9896.77790.06559921.638781.1403 9932.55775.5585
9954.375760.01279965.404746.16789976.721726.59849988.038719.13339999.361717.7373
10010.65722.7082 10021.9732.388510033.15 741.196 10044.4 751.42110055.24759.3025
10066.03 766.324 10098.4781.602110130.07 793.62710171.97807.1993 10182.3 812.416
10192.62816.586910202.94819.969710213.26824.317910244.23837.790810250.95841.3926
#Mann= 3 , 0 , 0
9749.058    0.04       09749.058    0.04       010250.95    0.04       0
#XS Ineff= 2 , 0
       0                               0
Bank Sta=9749.058,10250.95
Exp/Cntr=0.3,0.1

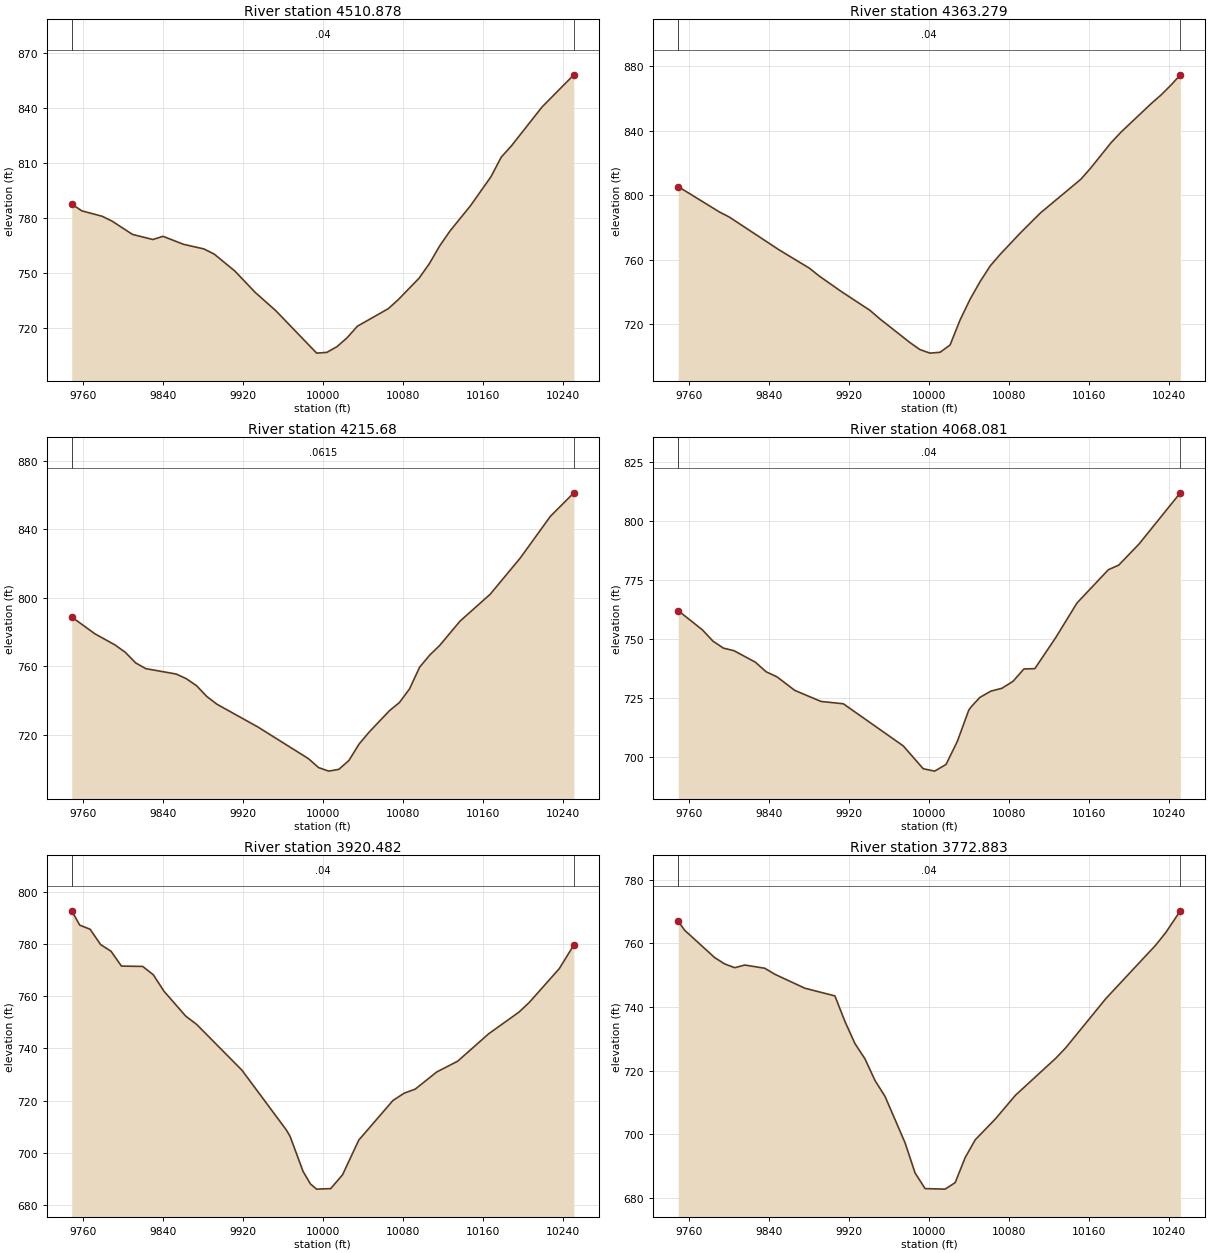
Type RM Length L Ch R = 1 ,4510.878,147.599000,147.599000,147.599000
XS GIS Cut Line= 6
726281.272032013797974.799237123726264.247831345797880.234749211
726237.944702725797766.174796493726223.931385816  797691.8074645
726195.440192556797571.753894199726176.772009766797483.951832276
#Sta/Elev= 30
9749.023787.7043 9758.98784.04299779.301781.09889789.462778.38229809.784771.1787
9830.105768.41479840.266 770.1589860.742765.79469881.267763.2733 9891.53760.4383
9912.055751.2591 9932.58739.51829953.104729.60139993.876706.531710004.05706.9376
10014.23710.078910024.41 714.95910034.59721.195210065.39730.711310075.67735.7718
10096.22747.3384 10106.5755.238410116.78764.855410127.06772.985410147.61786.7804
10168.13802.610610178.35813.241810188.58 819.42110219.25840.636410250.99 858.114
#Mann= 3 , 0 , 0
9749.023    0.04       09749.023    0.04       010250.99    0.04       0
#XS Ineff= 2 , 0
       0                               0
Bank Sta=9749.023,10250.99
Exp/Cntr=0.3,0.1

Type RM Length L Ch R = 1 ,4363.279,147.598900,147.598900,147.598900
XS GIS Cut Line= 6
726388.297452608797946.096872835726387.162703797797865.397241235
726382.641557003797783.112416553726373.913405093797696.684084357
726373.687695813797694.696861339726348.168051615797446.009934112
#Sta/Elev= 30
9749.016805.30269790.116789.59969800.117786.40029850.151765.91679880.196754.6359
9890.211749.67839912.132740.11739940.387728.60979950.438723.25979980.591708.4967
9988.186705.16989990.642704.104510000.69701.890210010.75 702.404 10020.8706.9436
10030.85722.542910040.91 735.48110050.96746.479910061.01756.114910071.06763.3585
10091.17776.611710111.27789.042510151.48809.859810161.54816.949710181.64832.5225
10191.69839.157910221.85856.8726 10231.9862.324110241.96868.577210250.99874.7585
#Mann= 3 , 0 , 0
9749.016    0.04       09749.016    0.04       010250.99    0.04       0
#XS Ineff= 2 , 0
       0                               0
Bank Sta=9749.016,10250.99
Exp/Cntr=0.3,0.1

Type RM Length L Ch R = 1 , 4215.68,147.599000,147.599000,147.599000
XS GIS Cut Line= 6
 726474.83072985797947.675008435726511.143380772797755.020110843
726520.447196632797699.859719771726523.639062013797679.309892516
 726540.39578925797555.673004175726548.929329593797451.608258548
#Sta/Elev= 30
9749.013788.64159772.088778.8692 9792.44772.27479802.616767.99779812.792761.8867
9822.968758.49449853.496755.32869863.672752.57759873.848748.47879884.024742.2093
9894.201737.68279934.905 724.4669985.646 705.8979995.787700.662210005.92698.6035
10016.04699.653210026.15704.860510036.24714.404410046.33721.418510066.51733.8433
 10076.6738.694110086.69746.635710096.79759.334110106.88766.399110116.97772.1204
10137.15 786.23110167.31801.936510197.41823.120610227.51847.468110250.98861.2119
#Mann= 3 , 0 , 0
9749.013  0.0615       09749.013  0.0615       010250.98  0.0615       0
#XS Ineff= 2 , 0
       0                               0
Bank Sta=9749.013,10250.98
Exp/Cntr=0.3,0.1

Type RM Length L Ch R = 1 ,4068.081,147.598900,147.598900,147.598900
XS GIS Cut Line= 6
726554.948230808797977.915770952726597.426623183797862.813514937
726677.432071073797713.204565333726704.039635492 797655.08249022
726724.192705596797594.608676658726740.462884711797514.536582841
#Sta/Elev= 30
9749.039761.90539773.151753.82389783.674749.06029794.196746.07449804.718744.9943
 9826.14740.13289836.968 736.0489847.797733.91889865.495728.20499891.729723.5295
9914.081722.53539974.027704.70399993.944695.059410005.37694.050110016.74696.8782
10028.11706.696210039.47719.850910041.51721.071310050.54725.219710061.54727.8757
10072.53729.078110083.72732.037710094.53737.251410105.52737.393210126.61750.6656
10147.69765.186410179.06779.242710189.35781.162910209.85790.188210250.93811.7512
#Mann= 3 , 0 , 0
9749.039    0.04       09749.039    0.04       010250.93    0.04       0
#XS Ineff= 2 , 0
       0                               0
Bank Sta=9749.039,10250.93
Exp/Cntr=0.3,0.1

Type RM Length L Ch R = 1 ,3920.482,147.598900,147.598900,147.598900
XS GIS Cut Line= 6
726660.553449296798062.636516764 726716.51531101797915.749696915
 726800.92348017797805.973992519726825.222629389797761.262434993
 726845.82775647797690.608099676726855.294773206 797610.50496951
#Sta/Elev= 30
 9749.05792.74999757.012787.26389767.438 785.6739777.864779.81939788.291777.2586
9798.717771.55979819.919771.4363 9830.54768.24269841.297761.88999863.027752.3561
9873.892749.19489919.075731.68219963.375 708.8069967.282 706.2689980.287692.8024
9987.651  688.019993.734686.035610007.85686.228710019.73691.544910035.94704.8397
10070.11720.029510081.32722.831810092.38724.383610113.79 730.93810134.82735.0983
10165.69745.572610196.13753.931810206.23757.571910236.36770.586810250.91779.6502
#Mann= 3 , 0 , 0
 9749.05    0.04       0 9749.05    0.04       010250.91    0.04       0
#XS Ineff= 2 , 0
       0                               0
Bank Sta=9749.05,10250.91
Exp/Cntr=0.3,0.1

Type RM Length L Ch R = 1 ,3772.883,147.599000,147.599000,147.599000
XS GIS Cut Line= 6
726922.916344346798121.482500307726920.597629356798025.297623934
726911.944346562797896.754417163726910.251544433 797850.94303233
726897.759731579797730.601477966726891.293278243797620.704108418
#Sta/Elev= 30
9749.015766.90179755.499764.07029785.508755.48519795.511753.50769805.514752.3334
9815.516753.17129835.522752.16129845.526750.28639875.594 745.8969905.662743.4804
9915.684735.46649925.707728.52149935.729723.72179945.752716.93279955.775711.9434
9975.817 697.3769985.824687.91689995.832 683.01410015.84682.851510025.88684.8871
10035.93692.772710045.99698.348210066.09704.8727 10086.2712.323910126.42723.9069
10136.47727.210310176.56 742.64710226.64759.503410236.66763.451210250.98770.1775
#Mann= 3 , 0 , 0
9749.015    0.04       09749.015    0.04       010250.98    0.04       0
#XS Ineff= 2 , 0
       0                               0
Bank Sta=9749.015,10250.98
Exp/Cntr=0.3,0.1

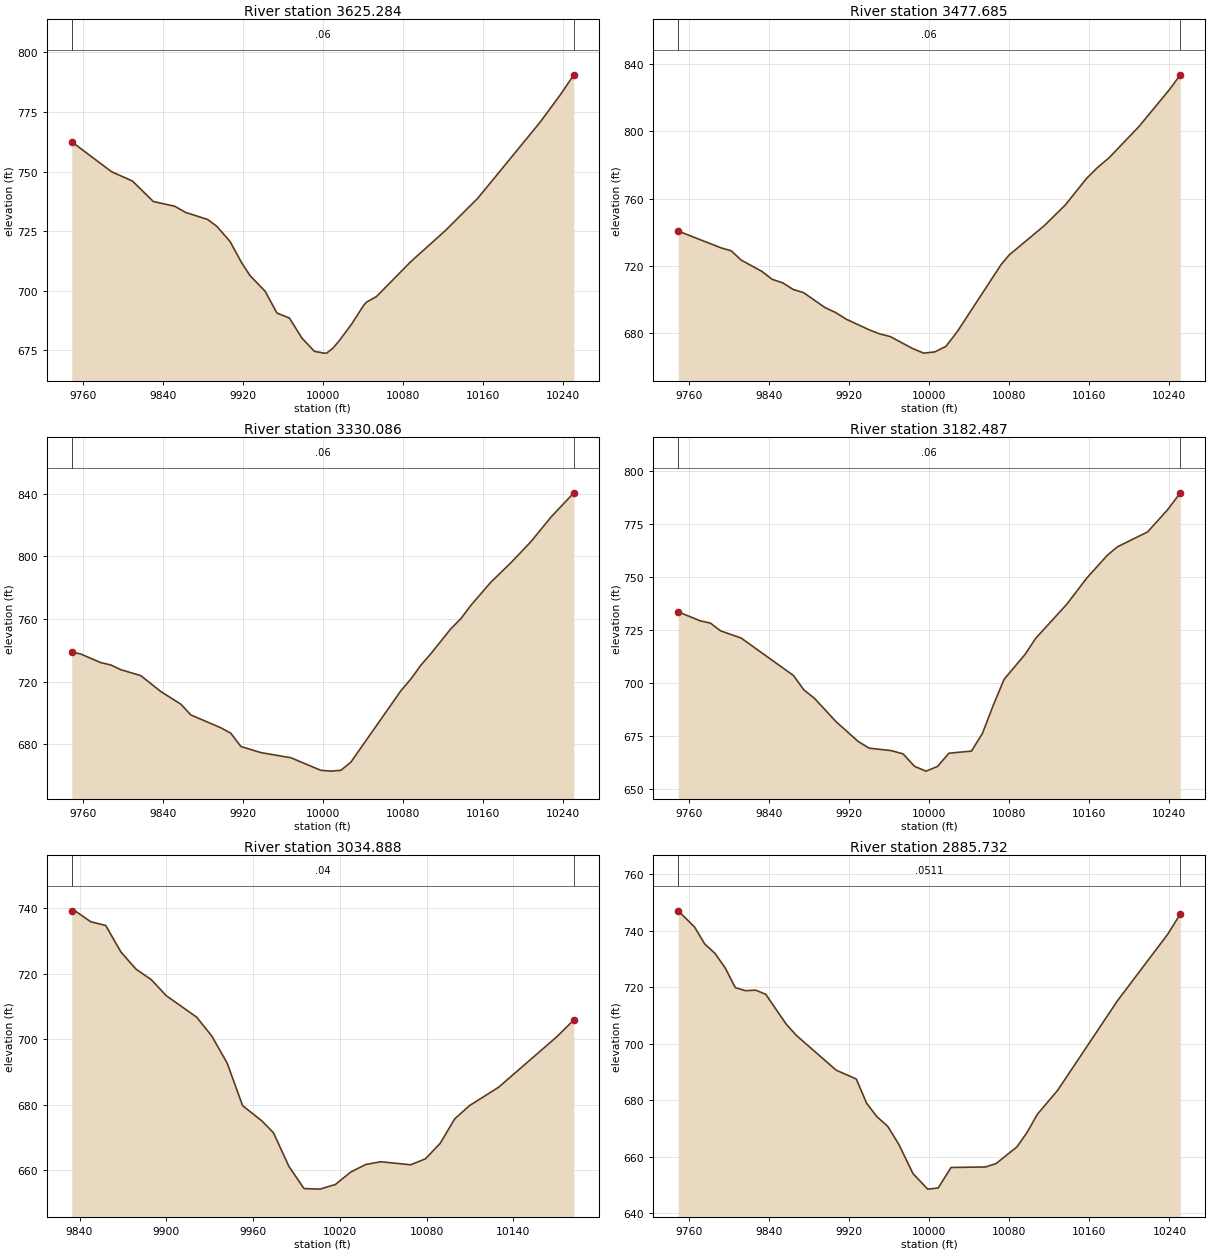
Type RM Length L Ch R = 1 ,3625.284,147.598900,147.598900,147.598900
XS GIS Cut Line= 6
727144.607657584798033.829464016727124.232669266797955.800252789
727099.327164136797896.711582536726977.924871077797710.530793421
726953.887148881797644.240475831726940.109625115797581.988697781
#Sta/Elev= 30
9749.043762.47379788.867 749.925 9809.67746.04879830.595737.44839851.971  735.47
9862.764732.88549884.779729.93459893.902727.12529907.313720.67749918.763711.8468
9927.215706.40749942.261699.87129954.185690.67799966.628688.59129979.083680.2124
9991.537674.6527   10001673.887510004.01673.913210010.26676.051510016.42679.0676
10028.83686.109110041.24694.171510044.04695.358710053.65697.607210087.85712.1981
10122.57725.294710154.94 738.83610217.12770.6554 10237.6782.300210250.93 790.562
#Mann= 3 , 0 , 0
9749.043    0.06       09749.043    0.06       010250.93    0.06       0
#XS Ineff= 2 , 0
       0                               0
Bank Sta=9749.043,10250.93
Exp/Cntr=0.3,0.1

Type RM Length L Ch R = 1 ,3477.685,147.598900,147.598900,147.598900
XS GIS Cut Line= 6
727236.632670415797957.049339629727225.490507888797894.267325211
727206.225830616797826.394634542727116.162341341797627.111738666
727091.317770836797553.720998642727074.196287405797484.548640167
#Sta/Elev= 30
9749.052740.62429791.758 730.6449801.914728.89839812.071723.29439832.677   716.6
9842.985711.85529853.427709.79589863.904 705.8459874.382703.93049895.672695.0791
9906.445692.04759917.217688.04199940.359681.67039949.862679.45279960.993 677.753
9983.255670.65499994.386667.887810005.54668.616510016.69671.933210027.85680.5626
10071.82720.677210079.94726.421410114.99743.8537 10136.1756.257710157.22771.9896
10167.78778.268410179.68784.273710209.27802.707210240.18825.004410250.94 833.738
#Mann= 3 , 0 , 0
9749.052    0.06       09749.052    0.06       010250.94    0.06       0
#XS Ineff= 2 , 0
       0                               0
Bank Sta=9749.052,10250.94
Exp/Cntr=0.3,0.1

Type RM Length L Ch R = 1 ,3330.086,147.599000,147.599000,147.599000
XS GIS Cut Line= 6
727296.915957548797944.018597708727301.756703047797694.066010748
727301.791011724797692.066305041727302.026773578797648.241296676
727299.670124064797551.643314453727293.835579247797442.259465986
#Sta/Elev= 30
9749.001738.97249758.021737.71889778.025732.20489788.026730.73529798.028 727.711
9818.032723.90619838.036713.7884 9858.04705.71859868.041698.84849898.047690.6519
9908.049687.15229918.051678.72649938.055674.8189 9968.06671.53469998.066663.5051
10008.07662.997810018.07663.512710028.07668.727710078.08714.280310088.08721.7759
10098.08730.600310108.09737.956310128.09 753.87610138.09760.289810148.11768.8289
10168.13783.601310188.16795.993410208.19809.457410228.22825.105710250.99840.5315
#Mann= 3 , 0 , 0
9749.001    0.06       09749.001    0.06       010250.99    0.06       0
#XS Ineff= 2 , 0
       0                               0
Bank Sta=9749.001,10250.99
Exp/Cntr=0.3,0.1

Type RM Length L Ch R = 1 ,3182.487,147.598900,147.598900,147.598900
XS GIS Cut Line= 6
727359.216586268797956.632753995727395.871823397797816.756625085
727461.930505359 797689.05077336727483.567096994797634.620345754
727499.928714058797563.753667077727508.257803562797482.466679632
#Sta/Elev= 30
9749.076733.41489771.082729.20389781.255728.11859791.428724.46579811.966 721.071
9864.188703.42259874.715696.58119885.242692.63849906.842681.59849928.825672.3388
9939.817669.12669962.338667.92079973.829666.4183 9985.32660.52289996.811658.2769
10008.28660.486710019.66  666.7310042.25667.742310053.18676.123310064.11689.5148
10074.79 701.57710096.03 713.51710106.41720.974910137.36736.962710157.75749.5389
10178.04760.162310188.13764.129210218.31771.168610238.38781.701210250.95789.5988
#Mann= 3 , 0 , 0
9749.076    0.06       09749.076    0.06       010250.95    0.06       0
#XS Ineff= 2 , 0
       0                               0
Bank Sta=9749.076,10250.95
Exp/Cntr=0.3,0.1

Type RM Length L Ch R = 1 ,3034.888,149.156600,149.156600,149.156600
XS GIS Cut Line= 6
727514.898377364797957.668279256727544.507434793797860.395745327
727576.140039479797776.346849122727586.869728644797737.722633705
727597.989422395797665.781204667727601.077560788797623.104674672
#Sta/Elev= 30
9834.649739.22519837.402739.07799847.721735.90149858.118734.75849868.604726.6853
9879.091721.40969889.578718.23369900.064713.29489921.037 706.7599931.524700.9772
9942.114692.73239952.792679.75769966.277675.02539974.147671.46239984.825661.2034
9994.797654.72319995.503654.425510006.22  654.2610016.91 655.66410027.56659.4734
10037.93661.770510048.31662.620610069.02661.695410079.19663.496910089.37668.2055
10099.52675.745910109.61679.728210129.77685.345510169.93700.717810181.86705.9206
#Mann= 3 , 0 , 0
9834.649    0.04       09834.649    0.04       010181.86    0.04       0
#XS Ineff= 2 , 0
       0                               0
Bank Sta=9834.649,10181.86
Exp/Cntr=0.3,0.1

Type RM Length L Ch R = 1 ,2885.732,149.156600,149.156600,149.156600
XS GIS Cut Line= 6
727715.907683131798020.977582919727736.559237171797844.789044432
727724.987776194797808.458159874727683.937615772797757.219619432
727665.413318591797712.541796811727651.966941724797542.472817773
#Sta/Elev= 30
9749.141747.05559765.435741.32849775.632735.3154 9785.83732.01589796.027726.8947
9806.225719.86219816.384718.80659826.504718.98419836.623717.51729856.862 707.052
9866.948703.04949907.044690.66249927.075687.55189937.317679.03939947.694674.2167
9958.486670.81439969.666664.39019983.809 654.0529998.488648.582110008.88648.9807
 10021.8656.245710056.22656.416110066.77657.627510087.63663.525310097.86668.6953
10108.06675.073610128.22683.501810188.37715.363110238.38738.804910250.91745.9566
#Mann= 3 , 0 , 0
9749.141  0.0511       09749.141  0.0511       010250.91  0.0511       0
#XS Ineff= 2 , 0
       0                               0
Bank Sta=9749.141,10250.91
Exp/Cntr=0.3,0.1

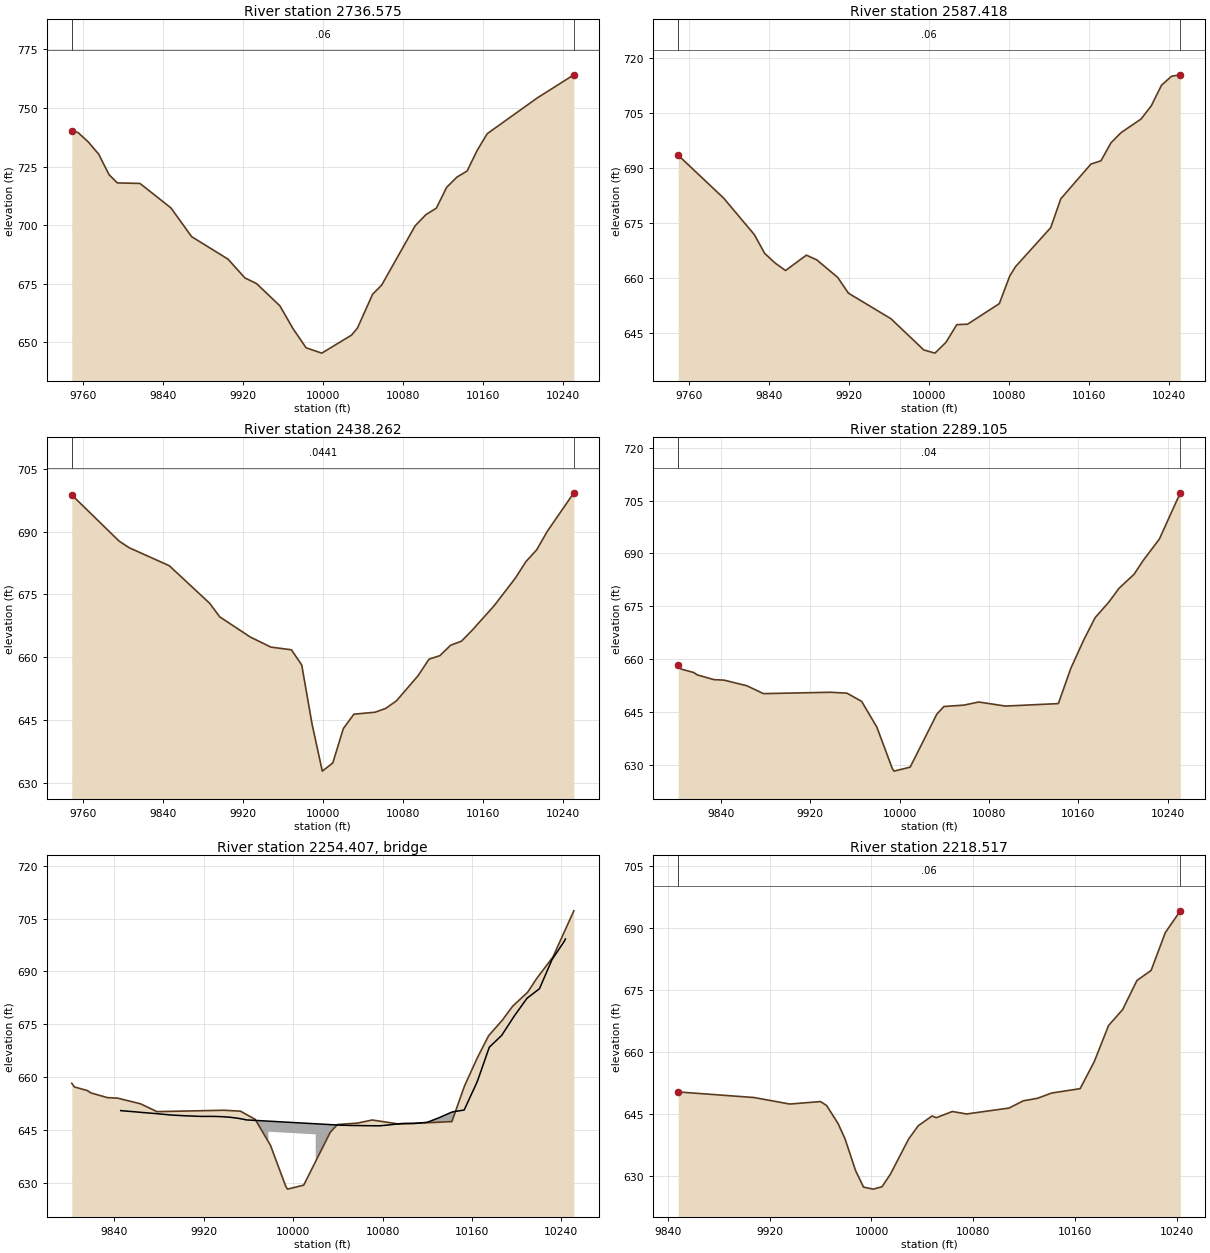
Type RM Length L Ch R = 1 ,2736.575,149.156700,149.156700,149.156700
XS GIS Cut Line= 6
727743.894698972  798011.0968108727790.476492229 797846.76629045
727867.451653798797742.862962499727891.569196384797692.749639587
727902.725641493797630.088186249727897.753837678797548.744133257
#Sta/Elev= 30
9749.103740.3109 9755.39739.47379765.701735.44329776.013 730.2649786.325721.5527
9794.618718.0291 9817.26717.78799848.195707.37279868.876 695.1149905.335685.4942
9922.146677.50889933.693675.12599957.102665.61849970.207655.89959983.313647.7144
    9999645.452210028.75653.139510034.69656.198910049.76670.561310058.77674.4199
10092.32699.751310103.08704.497410113.47707.248910123.76716.142610134.04720.4944
10144.24723.102410154.29 731.90210164.34739.001910214.43754.272310250.88764.0923
#Mann= 3 , 0 , 0
9749.103    0.06       09749.103    0.06       010250.88    0.06       0
#XS Ineff= 2 , 0
       0                               0
Bank Sta=9749.103,10250.88
Exp/Cntr=0.3,0.1

Type RM Length L Ch R = 1 ,2587.418,149.156600,149.156600,149.156600
XS GIS Cut Line= 6
727871.260962139798119.225912698727909.196560553797970.983058136
727960.266296638797845.411393281727980.035664555797780.132961382
727985.586573741797716.340275051727974.849079538797636.466098356
#Sta/Elev= 30
9749.054 693.5289794.426681.86019825.203671.87029835.494666.76769845.904664.1495
9856.314662.10619877.133666.30099887.543665.00889908.499660.22539919.148655.9389
9961.688648.96289994.481640.457410005.66639.587510016.72642.5465 10027.5647.3591
10038.27647.4733   10070653.083710080.39660.594810086.12663.136810121.37673.7934
10131.47681.673510161.57691.130610171.58692.021610181.61696.923210191.64699.6888
10211.78703.440710221.94707.032310232.09 712.61810242.25715.091810250.92715.4621
#Mann= 3 , 0 , 0
9749.054    0.06       09749.054    0.06       010250.92    0.06       0
#XS Ineff= 2 , 0
       0                               0
Bank Sta=9749.054,10250.92
Exp/Cntr=0.3,0.1

Type RM Length L Ch R = 1 ,2438.262,149.156600,149.156600,149.156600
XS GIS Cut Line= 6
728126.447794467798142.288481003728119.277514815798022.596721859
728109.984882961797967.773040386728092.385493727797893.512151533
728073.293072459797837.343302558728003.108650946797660.117094055
#Sta/Elev= 30
9749.046698.73569796.351687.72179806.354686.14539846.518681.84649886.871672.8926
9897.013669.63249927.483664.83379948.067 662.4269968.651661.78199978.943658.1589
9989.235644.09819999.512 632.83110009.99634.776710020.55642.991810031.11646.4131
10052.24646.885510062.86647.789110073.69649.615510095.35655.631410106.18659.5473
10117.01660.376810127.83662.876710138.66663.839310149.49 666.49310171.14672.2483
10192.46678.869910203.12 682.84110213.79685.625710224.45690.053810250.98699.2357
#Mann= 3 , 0 , 0
9749.046  0.0441       09749.046  0.0441       010250.98  0.0441       0
#XS Ineff= 2 , 0
       0                               0
Bank Sta=9749.046,10250.98
Exp/Cntr=0.3,0.1

Type RM Length L Ch R = 1 ,2289.105,70.587900,70.587900,70.587900
XS GIS Cut Line= 5
728335.192821205797926.623553976728224.084889084797824.357159376
728168.529333532797766.197437152728130.334889084797708.905770481
727998.390444666797639.461326048
#Sta/Elev= 30
9801.796 658.2599804.193657.22469815.649656.21869818.959655.53139833.725654.2027
9842.831654.05299863.258652.46019878.024650.22969937.969650.61839952.804650.3579
9965.956648.03139979.573 640.7269993.402 628.9919994.911 628.23710009.39629.3686
10033.23644.3882 10039.6646.574510057.62646.971110070.73647.850510094.77 646.696
10142.02647.400210153.32657.505110164.62665.372710174.89671.762410187.22676.2011
10196.36680.123710209.82684.106910217.83687.962310232.42 694.08110251.19707.2082
#Mann= 3 , 0 , 0
9801.796    0.04       09801.796    0.04       010251.19    0.04       0
#XS Ineff= 2 , 0
       0                               0
Bank Sta=9801.796,10251.19
Exp/Cntr=0.3,0.1

Type RM Length L Ch R = 3 ,2254.407,,,
BEGIN DESCRIPTION:
END DESCRIPTION:
Bridge Culvert--1,0,-1,-1, 0
Deck Dist Width WeirC Skew NumUp NumDn MinLoCord MaxHiCord MaxSubmerge Is_Ogee
14.952800,40.682300,2.6,0, 54, 54, , , 0.95, 0, 0,0,,
 9845.61 9851.54 9857.53 9864.53 9873.20 9877.52 9888.86 9890.51 9903.50 9904.53
 9916.49 9920.19 9929.48 9935.86 9942.48 9942.84 9950.40 9957.13 9957.45 9977.82
 9977.8210020.1410020.1410043.0410043.1310051.7110054.6510066.1710071.8310077.70
10077.7110085.6610096.8910099.6610108.1210119.3510121.6310130.5810141.8110143.61
10153.0410164.2710165.5810175.5110186.7410187.5510197.9710209.2010209.5310220.43
10231.5010231.6610242.8910243.60
  650.52  650.35  650.20  650.00  649.77  649.66  649.32  649.27  649.04  649.04
  648.88  648.87  648.87  648.80  648.66  648.65  648.35  647.96  647.89  647.53
  647.53  646.78  646.78  646.37  646.38  646.30  646.29  646.24  646.22  646.21
  646.21  646.45  646.86  646.89  646.88  647.18  647.40  648.50  650.08  650.20
  650.69  658.42  659.50  668.49  671.91  672.32  677.41  682.36  682.46  685.11
  693.26  693.38  698.70  699.23
 -349.48 -349.65 -349.80 -350.00 -350.23 -350.34 -350.68 -350.73 -350.96 -350.96
 -351.12 -351.13 -351.13 -351.20 -351.34 -351.35 -351.65 -352.04 -352.11 -352.47
  644.53  643.78 -353.22 -353.63 -353.62 -353.70 -353.71 -353.76 -353.78 -353.79
 -353.79 -353.55 -353.14 -353.11 -353.12 -352.82 -352.60 -351.50 -349.92 -349.80
 -349.31 -341.58 -340.50 -331.51 -328.09 -327.68 -322.59 -317.64 -317.54 -314.89
 -306.74 -306.62 -301.30 -300.77
 9845.61 9851.54 9857.53 9864.53 9873.20 9877.52 9888.86 9890.51 9903.50 9904.53
 9916.49 9920.19 9929.48 9935.86 9942.48 9942.84 9950.40 9957.13 9957.45 9985.70
 9985.7010028.0310028.0310043.0410043.1310051.7110054.6510066.1710071.8310077.70
10077.7110085.6610096.8910099.6610108.1210119.3510121.6310130.5810141.8110143.61
10153.0410164.2710165.5810175.5110186.7410187.5510197.9710209.2010209.5310220.43
10231.5010231.6610242.8910243.60
  650.52  650.35  650.20  650.00  649.77  649.66  649.32  649.27  649.04  649.04
  648.88  648.87  648.87  648.80  648.66  648.65  648.35  647.96  647.89  647.39
  647.39  646.64  646.64  646.37  646.38  646.30  646.29  646.24  646.22  646.21
  646.21  646.45  646.86  646.89  646.88  647.18  647.40  648.50  650.08  650.20
  650.69  658.42  659.50  668.49  671.91  672.32  677.41  682.36  682.46  685.11
  693.26  693.38  698.70  699.23
 -349.48 -349.65 -349.80 -350.00 -350.23 -350.34 -350.68 -350.73 -350.96 -350.96
 -351.12 -351.13 -351.13 -351.20 -351.34 -351.35 -351.65 -352.04 -352.11 -352.61
  644.39  643.64 -353.36 -353.63 -353.62 -353.70 -353.71 -353.76 -353.78 -353.79
 -353.79 -353.55 -353.14 -353.11 -353.12 -352.82 -352.60 -351.50 -349.92 -349.80
 -349.31 -341.58 -340.50 -331.51 -328.09 -327.68 -322.59 -317.64 -317.54 -314.89
 -306.74 -306.62 -301.30 -300.77
BR Coef=-1 , 0 , 0 ,, 0 ,,,0.8,0,1,0,
WSPro=,,,, 1 ,,,, 0 ,,,, 0 ,,,,-1 ,-1 ,-1 , 0 , 0 , 0 , 0 , 0
BC Design=,, 0 ,, 0 ,,,,,,

Type RM Length L Ch R = 1 ,2218.517,70.199400,70.199400,70.199400
XS GIS Cut Line= 5
728332.215573609797828.374383286728279.640444666797787.898826048
728211.064055771797715.850214943728196.307111353797681.996048257
728024.432111353797596.926603809
#Sta/Elev= 30
9848.151 650.3869907.737649.03569935.737647.4632 9959.92648.06359964.746647.1088
9973.725642.7778 9979.25639.04159987.531631.38319993.755627.422110001.34626.9311
10008.26627.4987 10014.9630.553610029.14638.991110036.71642.221110047.62644.5809
 10050.9644.165110063.52645.665610074.67645.065310108.15646.4984 10119.3648.2417
10130.46648.855610141.62650.128610163.94651.174310175.09657.719310186.25666.3923
10197.41670.287510208.57677.272110219.73 679.71210230.88688.830610242.67694.0913
#Mann= 3 , 0 , 0
9848.151    0.06       09848.151    0.06       010242.67    0.06       0
#XS Ineff= 2 , 0
       0                               0
Bank Sta=9848.151,10242.67
Exp/Cntr=0.3,0.1

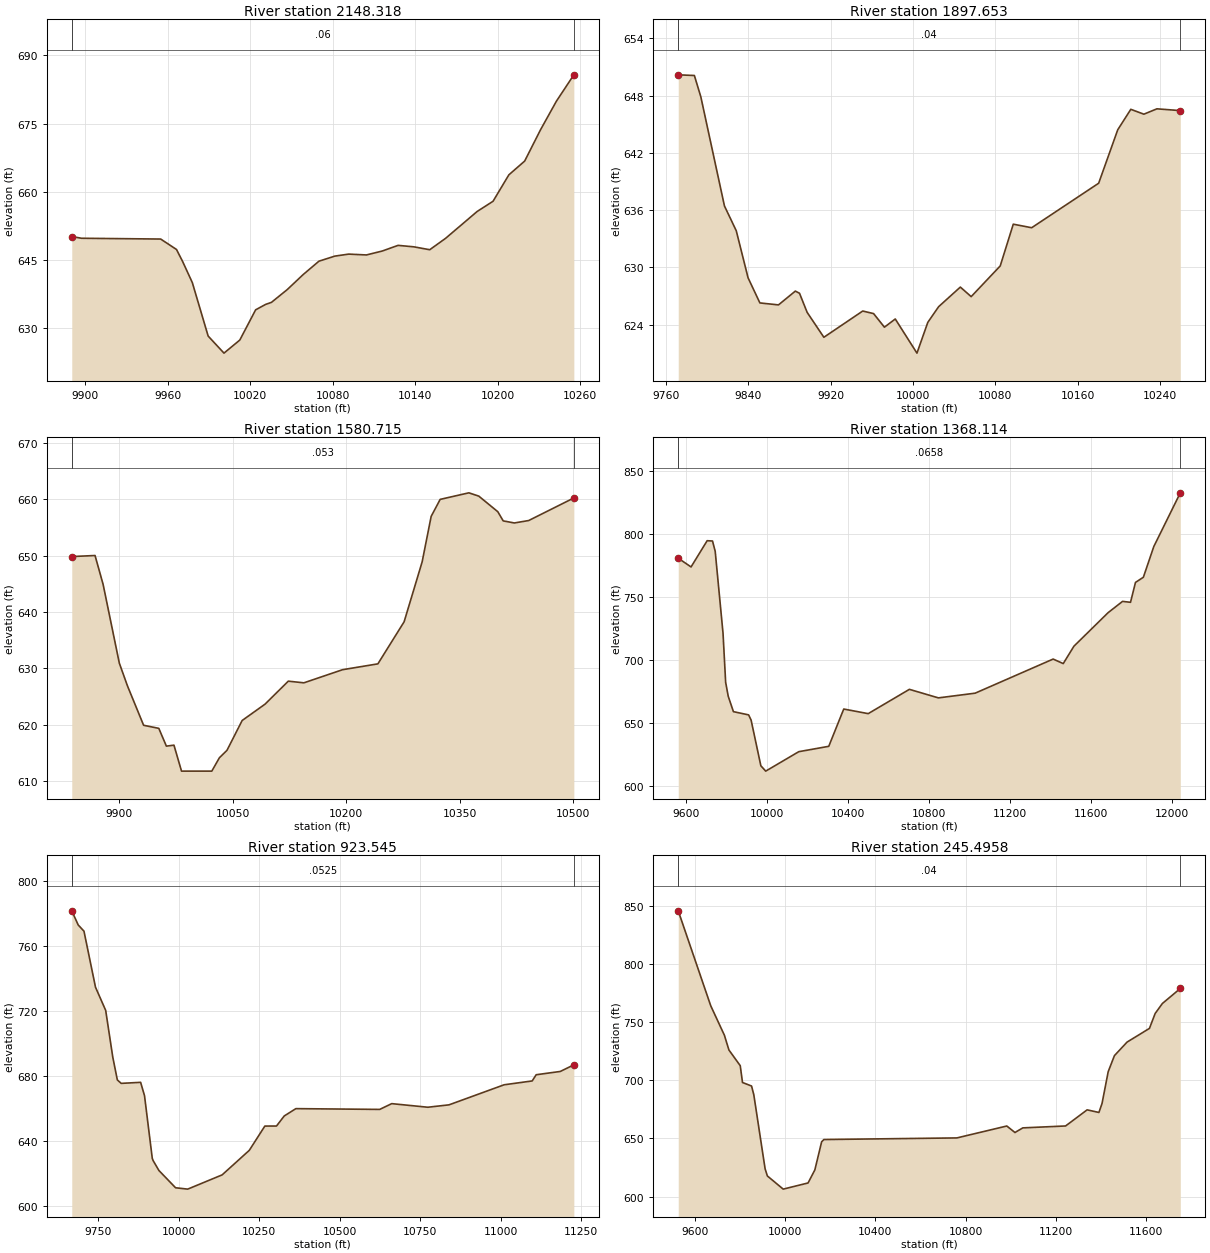
Type RM Length L Ch R = 1 ,2148.318,250.664400,250.664400,250.664400
XS GIS Cut Line= 2
728341.174763902797715.082362369728023.942897125797533.609111071
#Sta/Elev= 30
9890.044650.14769897.157 649.773 9954.76649.59999966.281647.30319970.766644.6436
9977.802640.01079989.322628.249710000.84624.495810012.36627.371410023.88634.0233
10031.18635.2218 10035.4635.668510046.93638.487410058.45 641.77410069.97644.7266
10081.49645.8402 10091.6646.284410104.53646.099210116.05646.963310127.57648.2097
10139.09647.885110150.61647.249910162.13649.751610185.17655.675410196.69657.9113
10208.21663.726710219.73666.764210231.26673.644910242.78 679.91810255.51685.7373
#Mann= 3 , 0 , 0
9890.044    0.06       09890.044    0.06       010255.51    0.06       0
#XS Ineff= 2 , 0
       0                               0
Bank Sta=9890.044,10255.51
Exp/Cntr=0.3,0.1

Type RM Length L Ch R = 1 ,1897.653,316.938500,316.938500,316.938500
XS GIS Cut Line= 4
728327.321843952797654.129514605728396.586443692797530.838527083
728348.101223886797383.997575656728197.104396492797266.247756109
#Sta/Elev= 30
9771.981650.16639787.657650.09579793.923647.86219816.863636.43049828.333633.8301
9839.803628.90259851.273626.27249869.324626.06549885.683627.51039889.741627.2858
9897.153625.28629913.396622.67339951.138625.42299961.669625.1548  9972.2623.7326
9982.731624.588310003.79621.013710014.32 624.23410024.86625.880310045.92627.9316
10056.45626.931910084.65630.146910097.33634.521110115.19634.148910180.24638.8113
10198.78644.413310211.46646.553410224.14646.043510236.82646.605310259.52646.4171
#Mann= 3 , 0 , 0
9771.981    0.04       09771.981    0.04       010259.52    0.04       0
#XS Ineff= 2 , 0
       09956.551        10065.13       0
Bank Sta=9771.981,10259.52
Exp/Cntr=0.3,0.1

Type RM Length L Ch R = 1 ,1580.715,212.600800,212.600800,212.600800
XS GIS Cut Line= 6
728316.239508003797687.376522467728406.206871957797653.334884211
728559.932456285797649.762843296728663.074311376797619.844501615
728779.401302785797553.405571193728908.030581474797440.540949985
#Sta/Elev= 30
9837.566649.82049868.316650.00549879.008644.87229900.392630.93969911.084626.9283
9932.468 619.9329952.552619.38629962.552616.23799972.553616.40849982.553611.8098
10022.56611.809810032.56614.172810042.59615.493510062.66620.780310092.87623.6732
10123.61627.746510144.16627.451610195.29629.777610241.95630.812810276.61638.2667
10300.42648.884410312.33656.943910324.24659.949510362.13661.110910375.25660.5256
10400.39657.761110407.47656.141310422.16655.770910441.15656.2021 10500.8660.2034
#Mann= 3 , 0 , 0
9837.566   0.053       09837.566   0.053       0 10500.8   0.053       0
#XS Ineff= 2 , 0
       0                               0
Bank Sta=9837.566,10500.8
Exp/Cntr=0.3,0.1

Type RM Length L Ch R = 1 ,1368.114,444.569200,444.569200,444.569200
XS GIS Cut Line= 6
728244.675133024798191.752154411728439.034868926797964.156448603
728572.714308411797771.417625293728679.623688549  797663.6437103
729329.638718128797221.222345382730144.968361229796628.643475279
#Sta/Elev= 30
9561.268780.66939624.585773.75389704.182794.55429730.648794.33119743.882786.1864
9782.666721.01379795.484682.30279808.302671.15859833.937658.97859909.038656.4152
9921.395652.24079969.406616.06939993.397611.809810156.82627.228310305.01631.4874
10379.01661.053410499.94657.411210703.32676.674710846.71 669.90211028.25673.6347
11413.55700.687711463.52697.102111516.17710.876711685.03737.4728 11756.4746.4337
11795.78745.711711820.39761.472711859.36 765.57911910.83789.912912041.85832.5413
#Mann= 3 , 0 , 0
9561.268  0.0658       09561.268  0.0658       012041.85  0.0658       0
#XS Ineff= 2 , 0
       0                               0
Bank Sta=9561.268,12041.85
Exp/Cntr=0.3,0.1

Type RM Length L Ch R = 1 , 923.545,678.049200,678.049200,678.049200
XS GIS Cut Line= 3
728693.813064307 798382.38566494729106.956029713 797769.02726239
729596.371542633797111.176540494
#Sta/Elev= 30
 9668.32781.60959688.344772.90779706.244 769.0779742.044734.5831 9773.68720.3101
9795.744691.50839809.851677.50799821.908675.38899882.193676.0307 9894.25667.8382
9918.364 629.2789921.044627.85329938.944621.76679990.706611.122610028.44610.2853
10135.39 619.05610219.79634.175610268.02649.103910304.19649.1256 10328.3  655.33
10364.47 659.83410624.75659.360410662.14  662.9110774.32660.696610840.15662.1719
11011.13674.514711098.38676.884811110.84680.705311185.62682.721211227.78686.8025
#Mann= 3 , 0 , 0
 9668.32  0.0525       0 9668.32  0.0525       011227.78  0.0525       0
#XS Ineff= 2 , 0
       0                               0
Bank Sta=9668.32,11227.78
Exp/Cntr=0.3,0.1

Type RM Length L Ch R = 1 ,245.4958,0.000000,0.000000,0.000000
XS GIS Cut Line= 6
729466.105901217798757.200741436729543.510861092797924.727427509
729635.207323272797593.667997909729742.725671173797386.024982783
729845.856147478797239.025563202730274.722088386796779.525097524
#Sta/Elev= 30
9527.075845.44239671.071763.87969731.458738.63749751.567725.93049801.738712.4297
9811.772 697.981 9851.84694.97569861.852687.44589911.912623.80889921.924617.7105
9992.008606.412810102.18611.712610132.23622.938710162.28647.0855 10172.3649.0012
 10761.4650.397910982.44660.625511018.57655.042311053.37659.014811242.85660.6627
 11338.2674.499811390.48672.258811404.18 679.92611431.58707.315311459.17 721.073
11515.08732.686211614.27 744.47411639.57757.270911671.54765.849111750.96778.7458
#Mann= 3 , 0 , 0
9527.075    0.04       09527.075    0.04       011750.96    0.04       0
#XS Ineff= 2 , 0
       0                               0
Bank Sta=9527.075,11750.96
Exp/Cntr=0.3,0.1